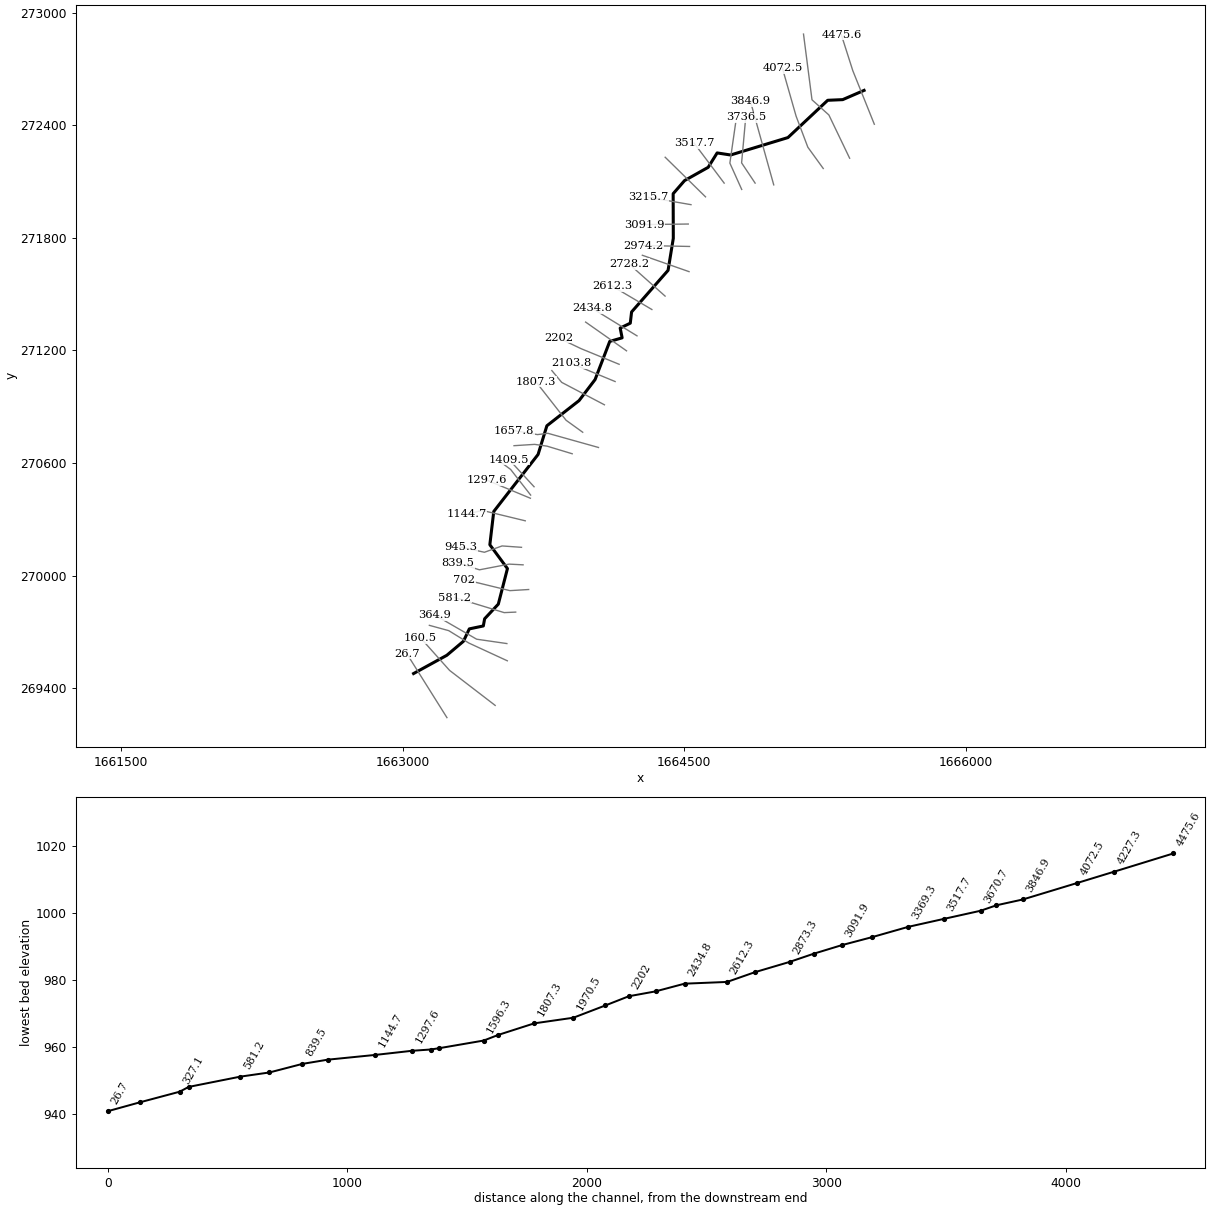
--- BUCKEYECK.prj (project) ---

Proj Title=BUCKEYECK
Current Plan=p01
Geom File=g01
Flow File=f01
Plan File=p01
DSS Export Rating Curves=0
DSS Export Rating Curve Sorted=0
DSS Export Volume Flow Curves=0
DXF OffsetX=0
DXF OffsetY=0
DXF ScaleX=0
DXF ScaleY=0

--- BUCKEYECK.p01 (plan) ---

Plan Title=Floodplain
Program Version=4.00
Geom File=g01
Flow File=f01
K Sum by GR=0
Std Step Tol=0.01
Critical Tol=0.01
Num of Std Step Trials=20
Max Error Tol=0.3
Flow Tol Ratio=0.001
Split Flow NTrial=30
Split Flow Tol=0.02
Split Flow Ratio=0.02
Log Output Level=0
Friction Slope Method=1
Unsteady Friction Slope Method=2
Unsteady Bridges Friction Slope Method=1
Global Log Level=0
CheckData=False
Run HTab=0
Run UNet=0
Run PostProcess=0
UNET Theta=0
UNET Theta Warmup=0
UNET ZTol=0
UNET ZSATol=0
UNET MxIter=0
UNET MaxInSteps=0
UNET DtIC=0
UNET DtMin=0
UNET MaxCRTS=0
UNET WFStab=0
UNET SFStab=0
UNET WFX=0
UNET SFX=0
UNET DSS MLevel=0
UNET DZMax Abort=0
UNET Convert EG Bridges=0
UNET Use Existing IB Tables=0
UNET Froude Limit=0
UNET Froude Power=0
Write IC File=0
Echo Input=False
Echo Output=False
Write Detailed=0

--- BUCKEYECK.f01 (steady flow) ---

Flow Title=NFF Regression Equation
Program Version=4.10
Number of Profiles= 1
Profile Names=P100yr
River Rch & RM=BUCKEYECK,Main            ,4475.6
197.9324
River Rch & RM=BUCKEYECK,Main            ,3517.7
222.3914
River Rch & RM=BUCKEYECK,Main            ,3215.7
246.5791
River Rch & RM=BUCKEYECK,Main            ,2612.3
252.7333
River Rch & RM=BUCKEYECK,Main            ,2314
278.6744
River Rch & RM=BUCKEYECK,Main            ,1409.5
294.6838
River Rch & RM=BUCKEYECK,Main            ,1144.7
  333.75
River Rch & RM=BUCKEYECK,Main            ,839.5
334.4181
River Rch & RM=BUCKEYECK,Main            ,581.2
337.9155
Boundary for River Rch & Prof#=BUCKEYECK,Main            , 1
Up Type= 0
Dn Type= 3
Dn Slope=0.01255
DSS Import GetInterval= 0
DSS Import GetPeak= 0
DSS Import FillOption= 0

--- BUCKEYECK.g01 (geometry) ---

Geom Title=USGS 10m DEM
Program Version=4.10

River Reach=BUCKEYECK       ,Main
Reach XY= 30
     1665458.026      272585.209     1665344.137      272535.903
     1665264.276      272532.431     1665052.471       272333.82
      1664747.23      272241.013     1664675.392      272252.042
     1664627.606      272175.397     1664501.794      272104.709
     1664441.059      272034.829     1664441.842      271797.272
     1664413.984      271626.616      1664219.62      271404.911
     1664212.675      271345.189     1664158.856      271319.147
     1664169.272      271267.064       1664103.3      271247.966
     1664025.175      271044.841     1663939.697      270932.608
     1663768.404      270798.661     1663721.529      270645.883
     1663485.418      270342.064     1663464.585       270164.98
     1663558.335      270037.897     1663509.724      269848.661
     1663436.807      269770.536     1663429.863      269732.341
      1663355.21      269716.716      1663323.96      269650.744
     1663235.418      269576.091     1663058.335      269478.869

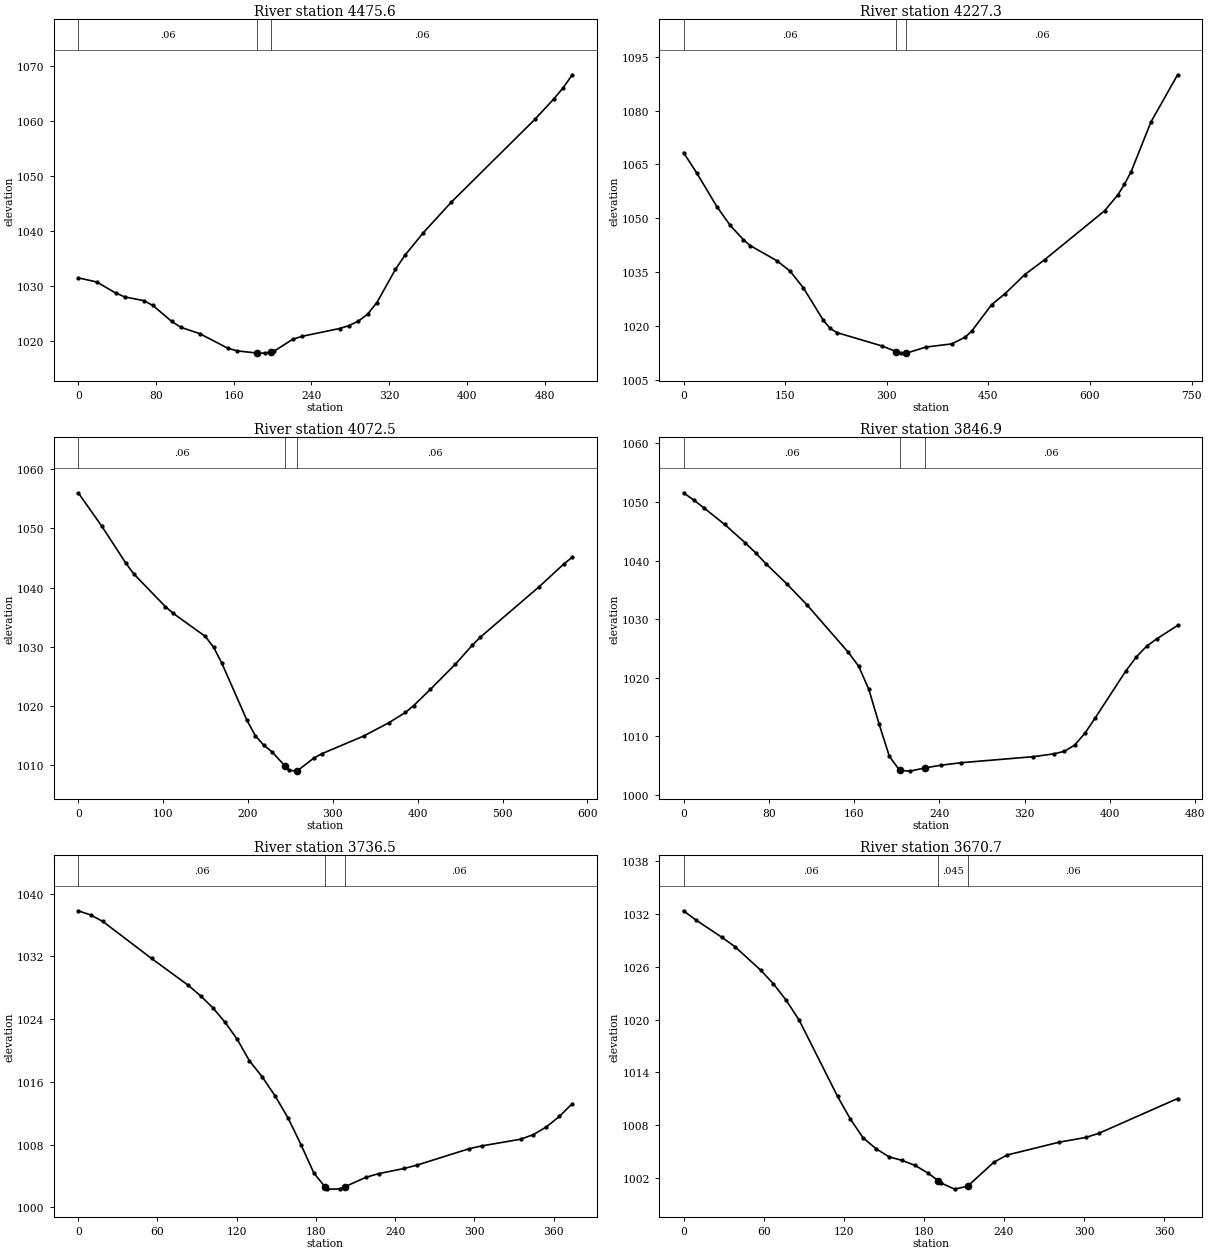
Type RM Length L Ch R = 1 ,4475.6  ,239.1,248.3,257.3
XS GIS Cut Line= 3
      1665512.65      272404.816     1665398.067      272689.972
     1665336.869      272881.378
#Sta/Elev= 30
       0 1031.51    19.2 1030.75    38.4 1028.76      48 1028.04    67.2 1027.38
    76.8  1026.5      96 1023.62   105.6 1022.52   124.8 1021.39   153.7 1018.75
   163.3 1018.25   183.8 1017.86   192.1 1017.84   198.8 1018.11   201.7 1018.23
   220.9 1020.37   230.5  1020.9   268.9 1022.31   278.5 1022.83   288.1 1023.63
   297.7  1024.9   307.3 1027.03   326.4 1033.05     336 1035.58   355.2 1039.73
   383.9 1045.26     470 1060.31   489.1 1063.95   498.7 1065.96   508.3 1068.37
#Mann= 3 , 0 , 0
       0     .06       0   183.8    .045       0   198.8     .06       0
Bank Sta=183.8,198.8
XS Rating Curve= 0 ,0
Exp/Cntr=0.3,0.1

Type RM Length L Ch R = 1 ,4227.3  ,165.7,154.8,143.9
XS GIS Cut Line= 4
      1665381.14      272223.826     1665270.463      272454.295
     1665180.619      272535.024     1665135.387      272885.105
#Sta/Elev= 30
       0  1068.3    19.7 1062.55    49.2 1053.24    68.8 1048.02    88.5 1043.97
    98.3 1042.38   137.7 1038.15   157.3 1035.24     177 1030.54   206.5 1021.48
   216.3 1019.28   226.2  1018.1   292.8 1014.37   314.1 1012.78   320.7 1012.36
   329.1 1012.36   357.9 1014.05   396.1 1014.94   415.7 1016.79   425.5  1018.5
   454.9  1025.9   474.5 1028.91   503.9 1034.28   533.3 1038.44   621.6 1052.06
   641.2 1056.49     651 1059.47   660.8 1062.97   690.2 1076.88   729.4    1090
#Mann= 3 , 0 , 0
       0     .06       0   314.1    .045       0   329.1     .06       0
Bank Sta=314.1,329.1
XS Rating Curve= 0 ,0
Exp/Cntr=0.3,0.1

Type RM Length L Ch R = 1 ,4072.5  ,227.4,225.6,223.7
XS GIS Cut Line= 4
     1665240.515      272169.139     1665158.483       272282.42
     1665095.983      272447.785     1665023.067      272702.993
#Sta/Elev= 30
       0    1056      28 1050.31      56 1044.13    65.3 1042.32   102.6 1036.78
   111.9 1035.63   149.7 1031.74   159.5  1029.9   169.3 1027.18   198.8 1017.56
   208.6 1014.97   218.4 1013.38   228.2 1012.24   243.3  1009.9   247.9 1009.13
   257.7 1008.97   258.3 1009.04   277.4 1011.16   287.2 1011.92   336.3  1014.9
   365.8 1017.13   385.5 1018.88   395.3 1020.05     415  1022.8   444.4 1027.04
   464.1 1030.22   473.9 1031.62   542.7 1040.08   572.2 1043.98   582.1 1045.12
#Mann= 3 , 0 , 0
       0     .06       0   243.3    .045       0   258.3     .06       0
Bank Sta=243.3,258.3
XS Rating Curve= 0 ,0
Exp/Cntr=0.3,0.1

Type RM Length L Ch R = 1 ,3846.9  ,118.9,110.4,101.8
XS GIS Cut Line= 2
     1664976.813      272081.876     1664852.176      272528.293
#Sta/Elev= 30
       0 1051.55     9.7  1050.3    19.3 1048.96    38.6 1046.15    57.9 1043.02
    67.6 1041.32    77.2 1039.47    96.6 1036.07   115.9 1032.42   154.5 1024.36
   164.2    1022   173.8 1018.04   183.5 1012.09   193.1  1006.6   202.8 1004.19
   212.4 1004.07   226.1  1004.6   241.4 1005.08   260.7 1005.51   328.3 1006.54
   347.6 1007.02   357.3 1007.45   366.9  1008.5   376.6 1010.54   386.2 1013.14
   415.2 1021.22   424.9 1023.56   434.5 1025.39   444.2 1026.66   463.5 1028.92
#Mann= 3 , 0 , 0
       0     .06       0   202.8    .045       0   226.1     .06       0
Bank Sta=202.8,226.1
XS Rating Curve= 0 ,0
Exp/Cntr=0.3,0.1

Type RM Length L Ch R = 1 ,3736.5  ,67.1,65.9,63.6
XS GIS Cut Line= 3
     1664877.616      272091.337     1664805.619      272199.087
     1664827.754      272442.576
#Sta/Elev= 30
       0  1037.8     9.3 1037.28    18.5 1036.46    55.5 1031.73    83.3 1028.31
    92.6 1026.97   101.8 1025.47   111.1 1023.61   120.3 1021.45   129.6  1018.7
   139.4 1016.62   149.2 1014.17   158.9  1011.4   168.7 1007.99   178.5 1004.36
   186.9 1002.62   188.3 1002.33     198 1002.35   201.9 1002.63   217.6 1003.82
   227.4  1004.3     247 1004.97   256.7  1005.4   295.8 1007.47   305.6 1007.84
     335 1008.69   344.7 1009.28   354.5 1010.26   364.3 1011.59   374.1 1013.22
#Mann= 3 , 0 , 0
       0     .06       0   186.9    .045       0   201.9     .06       0
Bank Sta=186.9,201.9
XS Rating Curve= 0 ,0
Exp/Cntr=0.3,0.1

Type RM Length L Ch R = 1 ,3670.7  ,134.3,153,170.6
XS GIS Cut Line= 3
     1664806.218      272057.483     1664743.126      272197.833
     1664773.898       272411.81
#Sta/Elev= 26
       0 1032.38     9.6  1031.3    28.8 1029.36    38.5  1028.3    57.7 1025.64
    67.3 1024.08    76.9  1022.2    86.6 1019.94   115.4 1011.25     125 1008.67
   134.6 1006.52   144.3 1005.29   153.9 1004.38   163.7 1003.97   173.5  1003.4
   183.4  1002.5     191 1001.63   193.2 1001.38     203  1000.7   212.8 1001.03
   232.5 1003.76   242.3 1004.58   281.6 1006.05   301.3 1006.58   311.1 1007.05
   370.1 1011.01
#Mann= 3 , 0 , 0
       0     .06       0     191    .045       0   212.8     .06       0
Bank Sta=191,212.8
XS Rating Curve= 0 ,0
Exp/Cntr=0.3,0.1

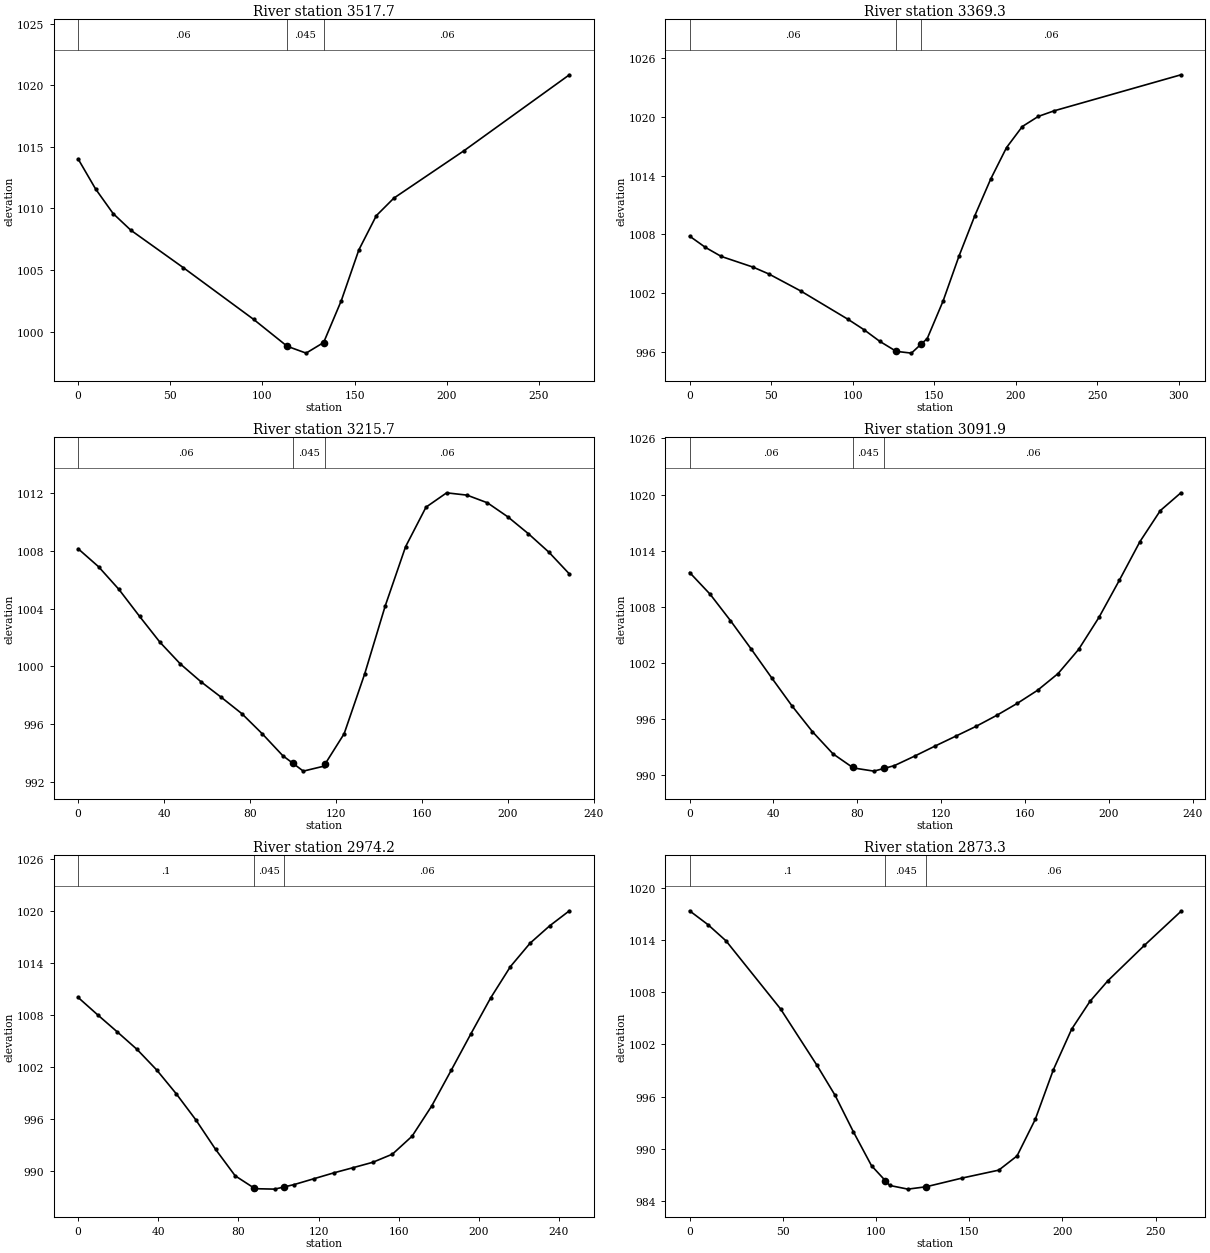
Type RM Length L Ch R = 1 ,3517.7  ,145,148.4,153.2
XS GIS Cut Line= 2
     1664712.762      272091.276     1664552.648      272304.284
#Sta/Elev= 15
       0 1014.02     9.5 1011.58      19 1009.59    28.6 1008.24    57.1  1005.2
    95.2 1001.01   113.4  998.83   123.7  998.27   133.2  999.13   142.8 1002.53
   152.3 1006.64   161.8 1009.42   171.3 1010.84   209.4 1014.69   266.5 1020.84
#Mann= 3 , 0 , 0
       0     .06       0   113.4    .045       0   133.2     .06       0
Bank Sta=113.4,133.2
XS Rating Curve= 0 ,0
Exp/Cntr=0.3,0.1

Type RM Length L Ch R = 1 ,3369.3  ,139.6,153.6,167
XS GIS Cut Line= 2
     1664613.441      272018.084     1664398.508      272229.083
#Sta/Elev= 22
       0 1007.83     9.7 1006.68    19.4 1005.76    38.9 1004.67    48.6 1003.97
      68 1002.25    97.2  999.34   106.9  998.29   116.6   997.1   126.7  996.08
     136   995.9   141.7  996.78   145.7  997.39   155.4 1001.21   165.2 1005.81
   174.9 1009.93   184.6 1013.65   194.3 1016.86     204 1019.01   213.8 1020.04
   223.5 1020.61   301.2 1024.28
#Mann= 3 , 0 , 0
       0     .06       0   126.7    .045       0   141.7     .06       0
Bank Sta=126.7,141.7
XS Rating Curve= 0 ,0
Exp/Cntr=0.3,0.1

Type RM Length L Ch R = 1 ,3215.7  ,119.6,123.8,128.1
XS GIS Cut Line= 2
     1664536.088       271976.43     1664310.827      272015.493
#Sta/Elev= 27
       0 1008.13     9.5 1006.89      19 1005.32    28.6 1003.46    38.1 1001.67
    47.6 1000.17    57.2  998.94    66.7  997.86    76.2  996.74    85.7  995.35
    95.3  993.83    99.9  993.32   104.8  992.77   114.3  993.11   114.9  993.25
   123.8  995.35   133.4   999.5   142.9 1004.17   152.4 1008.27   161.9    1011
   171.5 1011.99     181 1011.83   190.5  1011.3     200 1010.33   209.6 1009.16
   219.1 1007.89   228.6 1006.39
#Mann= 3 , 0 , 0
       0     .06       0    99.9    .045       0   114.9     .06       0
Bank Sta=99.9,114.9
XS Rating Curve= 0 ,0
Exp/Cntr=0.3,0.1

Type RM Length L Ch R = 1 ,3091.9  ,118.4,117.7,116.8
XS GIS Cut Line= 2
     1664521.619      271873.316     1664287.244      271870.324
#Sta/Elev= 27
       0 1011.67     9.8 1009.34    19.5 1006.52    29.3 1003.51    39.1 1000.42
    48.8  997.42    58.6  994.65    68.4  992.28    77.8  990.82    78.1  990.77
    87.9  990.43    92.8  990.72    97.7  991.02   107.4  992.04   117.2  993.12
     127  994.17   136.7  995.22   146.5  996.39   156.3  997.67     166  999.07
   175.8 1000.86   185.6 1003.44   195.3 1006.86   205.1 1010.86   214.9 1014.98
   224.6 1018.29   234.4 1020.19
#Mann= 3 , 0 , 0
       0     .06       0    77.8    .045       0    92.8     .06       0
Bank Sta=77.8,92.8
XS Rating Curve= 0 ,0
Exp/Cntr=0.3,0.1

Type RM Length L Ch R = 1 ,2974.2  ,107.8,100.9,93.3
XS GIS Cut Line= 2
     1664528.387      271753.825     1664283.272      271758.898
#Sta/Elev= 28
       0    1010     9.8 1007.98    19.6 1006.01    29.4    1004    39.2 1001.63
      49  998.87    58.8  995.85    68.6  992.46    78.4   989.4      88  987.96
    88.3  987.91    98.1  987.86     103  988.12   107.9  988.39   117.7  989.06
   127.5  989.73   137.3  990.34   147.1  990.96   156.9   991.9   166.7  993.97
   176.5  997.46   186.3 1001.61   196.1 1005.81   205.9 1009.93   215.8 1013.56
   225.6 1016.26   235.4 1018.27   245.2    1020
#Mann= 3 , 0 , 0
       0      .1       0      88    .045       0     103     .06       0
Bank Sta=88,103
XS Rating Curve= 0 ,0
Exp/Cntr=0.3,0.1

Type RM Length L Ch R = 1 ,2873.3  ,153.7,145,136.2
XS GIS Cut Line= 2
     1664525.671       271619.66     1664276.973      271706.899
#Sta/Elev= 22
       0 1017.34     9.8 1015.76    19.5  1013.9    48.8 1006.08    68.3  999.62
    78.1  996.15    87.8  992.01    97.6  988.09     105 986.376   107.4  985.82
   117.1   985.4   126.9  985.67   146.4  986.68   165.9  987.58   175.7  989.21
   185.5  993.42   195.2  999.11     205 1003.76   214.8 1006.94   224.5 1009.33
     244 1013.37   263.6 1017.27
#Mann= 3 , 0 , 0
       0      .1       0     105    .045       0   126.9     .06       0
Bank Sta=105,126.9
XS Rating Curve= 0 ,0
Exp/Cntr=0.3,0.1

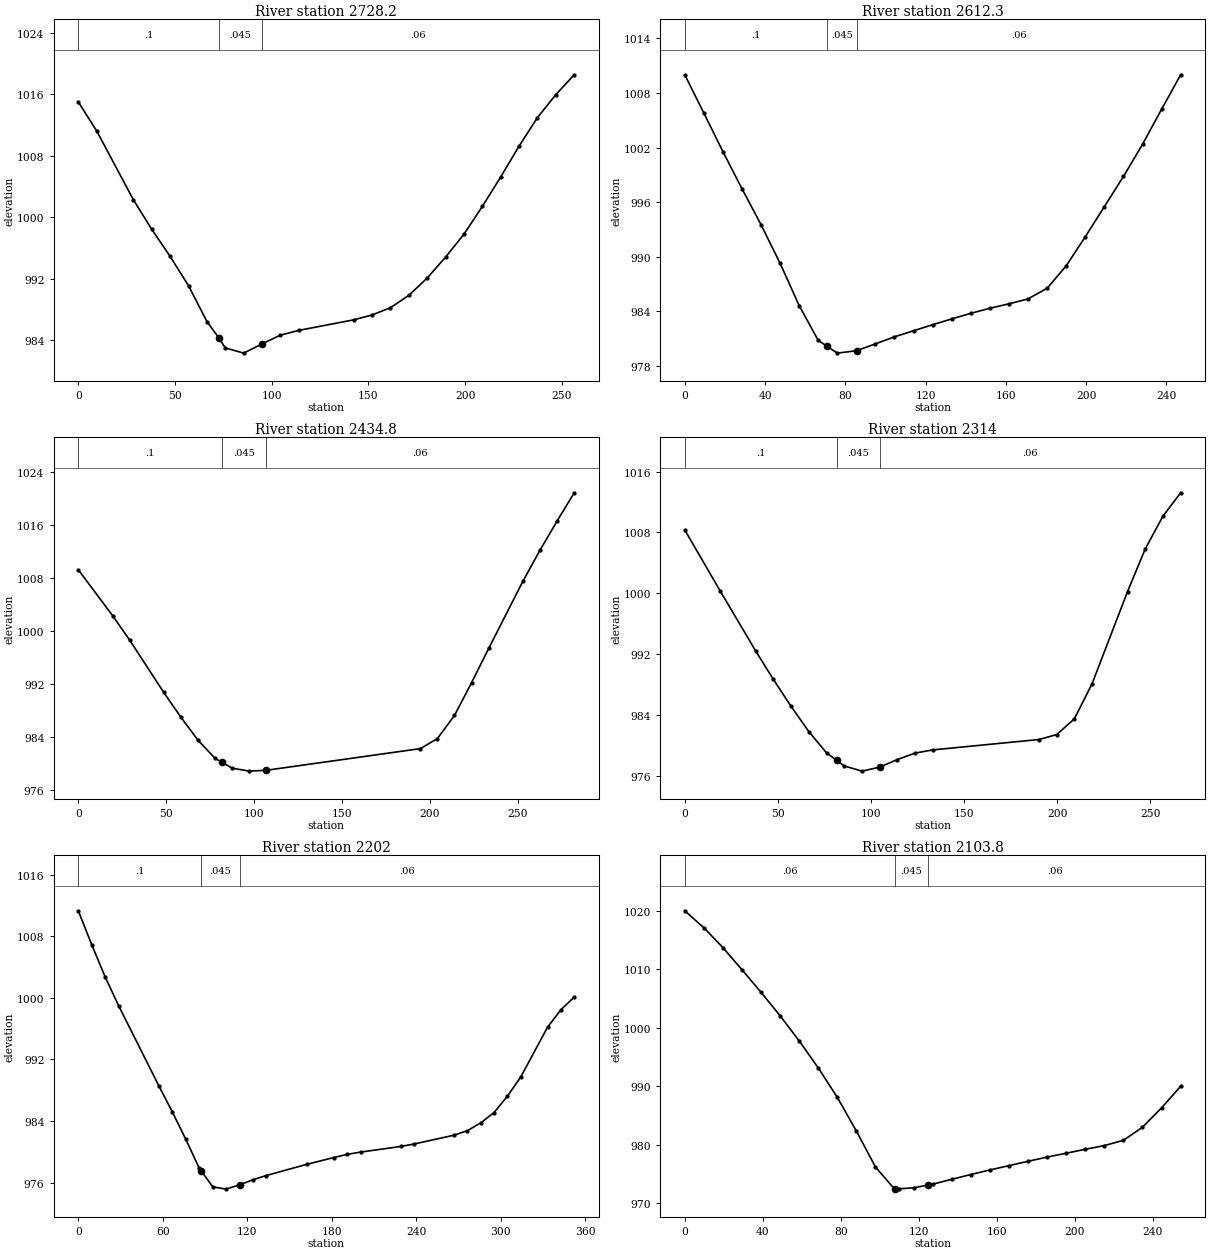
Type RM Length L Ch R = 1 ,2728.2  ,111.2,115.9,120.3
XS GIS Cut Line= 2
     1664398.067      271489.451     1664206.661      271660.024
#Sta/Elev= 26
       0    1015     9.5 1011.23    28.5 1002.26      38  998.42    47.5   994.9
      57  991.09    66.5  986.44   72.68   984.3      76  983.01    85.5  982.33
      95  983.53   104.4  984.66     114  985.29   142.4  986.66   151.9  987.29
   161.4  988.24   170.9  989.84   180.4   992.1   189.9  994.82   199.4  997.79
   208.9 1001.41   218.4 1005.24   227.9 1009.25   237.4 1012.96   246.9 1015.95
   256.4 1018.53
#Mann= 3 , 0 , 0
       0      .1       0   72.68    .045       0      95     .06       0
Bank Sta=72.68,95
XS Rating Curve= 0 ,0
Exp/Cntr=0.3,0.1

Type RM Length L Ch R = 1 ,2612.3  ,175.7,177.6,178.6
XS GIS Cut Line= 2
     1664327.715      271417.944     1664114.883      271543.433
#Sta/Elev= 29
       0    1010     9.5  1005.8      19 1001.56    28.5  997.48      38  993.53
    47.5  989.29      57  984.64    66.5  980.82    70.8  980.19      76  979.42
    85.5  979.68    85.8   979.7      95  980.44   104.5  981.21     114  981.88
   123.5  982.54     133  983.18   142.5  983.79     152  984.35   161.6  984.84
     171  985.37   180.6  986.55   190.1  989.02   199.6  992.21   209.1  995.52
   218.6  998.83   228.1 1002.36   237.6 1006.21   247.1    1010
#Mann= 3 , 0 , 0
       0      .1       0    70.8    .045       0    85.8     .06       0
Bank Sta=70.8,85.8
XS Rating Curve= 0 ,0
Exp/Cntr=0.3,0.1

Type RM Length L Ch R = 1 ,2434.8  ,117.1,120.8,121.8
XS GIS Cut Line= 2
     1664248.562      271277.643     1664008.124      271425.203
#Sta/Elev= 20
       0 1009.21    19.5 1002.31    29.2  998.63    48.6  990.75    58.4     987
    68.1  983.55    77.8  980.82    81.7  980.23    87.6  979.34    97.3   978.9
     107  979.03   194.6  982.29   204.3   983.8     214  987.28   223.7   992.2
   233.5  997.39   252.9 1007.47   262.6 1012.13   272.4 1016.56   282.1  1020.8
#Mann= 3 , 0 , 0
       0      .1       0    81.7    .045       0     107     .06       0
Bank Sta=81.7,107
XS Rating Curve= 0 ,0
Exp/Cntr=0.3,0.1

Type RM Length L Ch R = 1 ,2314    ,106.3,111.9,111.7
XS GIS Cut Line= 2
     1664192.633      271197.906     1663974.819      271351.004
#Sta/Elev= 22
       0 1008.32      19  1000.3      38  992.43    47.5  988.69      57  985.14
    66.6   981.8    76.1     979    81.5  978.02    85.6  977.28    95.1   976.6
   104.6  977.12   114.1  978.12   123.6  978.97   133.1  979.39   190.2  980.76
   199.7  981.41   209.2  983.49   218.7  988.12   237.7 1000.22   247.2 1005.83
   256.7 1010.14   266.2 1013.21
#Mann= 3 , 0 , 0
       0      .1       0    81.5    .045       0   104.6     .06       0
Bank Sta=81.5,104.6
XS Rating Curve= 0 ,0
Exp/Cntr=0.3,0.1

Type RM Length L Ch R = 1 ,2202    ,98.2,98.2,97.8
XS GIS Cut Line= 3
     1664153.275       271126.17      1663950.15      271209.503
     1663830.358      271266.795
#Sta/Elev= 29
       0  1011.3     9.6 1006.86    19.1  1002.7    28.6  998.98    57.3  988.53
    66.8  985.17    76.4   981.6    85.9  977.87    87.2  977.54    95.5  975.44
     105  975.14   114.6   975.7   124.1  976.36   133.6  976.91   162.3  978.36
   181.4  979.24   190.9  979.65   200.5  979.95     229  980.68   238.5     981
     267  982.15   276.5  982.74     286  983.76   295.4  985.09   304.9  987.22
   314.4  989.73   333.4  996.18   342.9  998.45   352.3 1000.08
#Mann= 3 , 0 , 0
       0      .1       0    87.2    .045       0   114.6     .06       0
Bank Sta=87.2,114.6
XS Rating Curve= 0 ,0
Exp/Cntr=0.3,0.1

Type RM Length L Ch R = 1 ,2103.8  ,134.9,133.3,131.6
XS GIS Cut Line= 2
     1664131.877      271034.319     1663896.897      271131.506
#Sta/Elev= 29
       0    1020     9.8  1017.1    19.6 1013.69    29.3 1009.93    39.1 1006.06
    48.9 1002.04    58.7  997.73    68.5   993.1    78.2  988.09      88  982.32
    97.8  976.16   107.6  972.38   109.8  972.43   117.4  972.61   124.8  973.08
   127.1  973.22   136.9  974.06   146.7  974.88   156.5  975.66   166.3   976.4
     176  977.14   185.8  977.86   195.6  978.52   205.4   979.2   215.2  979.83
     225  980.74   234.7  982.96   244.5  986.28   254.3  989.97
#Mann= 3 , 0 , 0
       0     .06       0   107.6    .045       0   124.8     .06       0
Bank Sta=107.6,124.8
XS Rating Curve= 0 ,0
Exp/Cntr=0.3,0.1

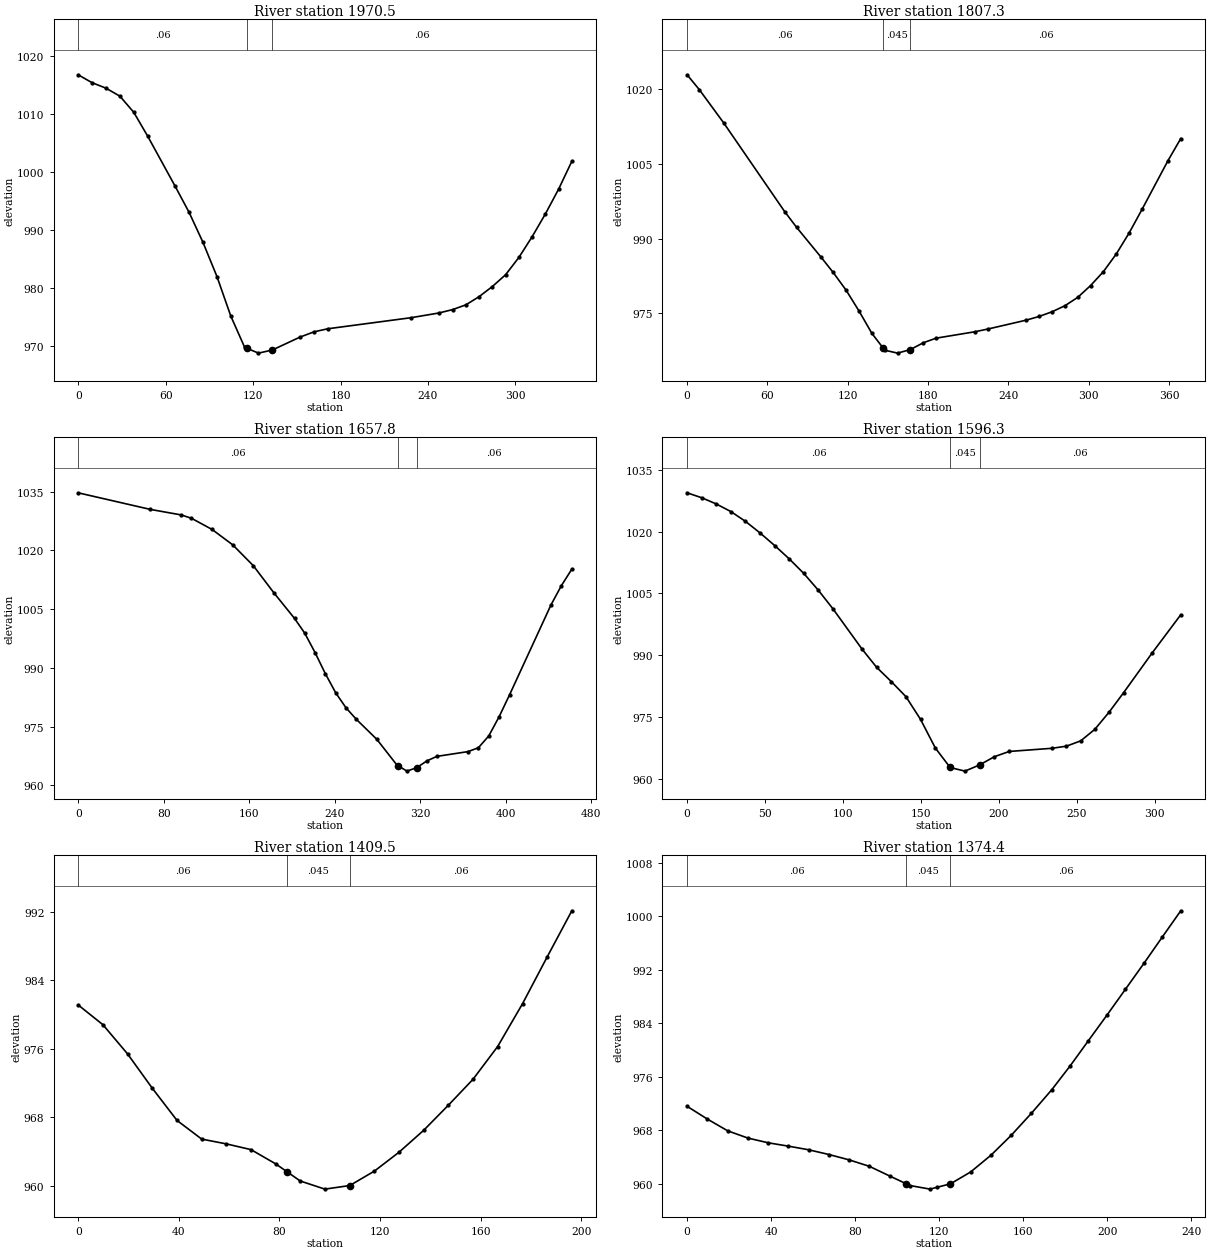
Type RM Length L Ch R = 1 ,1970.5  ,172.8,163.2,153.5
XS GIS Cut Line= 3
     1664074.782      270910.501     1663847.287       271029.88
     1663794.866      271092.661
#Sta/Elev= 30
       0  1016.8     9.5 1015.44      19  1014.5    28.6 1013.11    38.1 1010.33
    47.6 1006.23    66.6  997.51    76.1  993.03    85.6  987.86    95.2  981.95
   104.7  975.12   114.2  969.72   115.7  969.56   123.7  968.72   133.2  969.26
   152.2  971.49   161.8   972.4   171.3  972.93   228.4  974.84   247.4  975.65
   256.9  976.24     266  977.06   275.1  978.48   284.2  980.23   293.3  982.27
   302.4  985.26   311.4   988.8   320.5  992.74   329.6  997.03   338.7 1001.85
#Mann= 3 , 0 , 0
       0     .06       0   115.7    .045       0   133.2     .06       0
Bank Sta=115.7,133.2
XS Rating Curve= 0 ,0
Exp/Cntr=0.3,0.1

Type RM Length L Ch R = 1 ,1807.3  ,126,149.6,173.1
XS GIS Cut Line= 3
     1663959.265      270764.191     1663870.723      270827.993
     1663710.664      271032.309
#Sta/Elev= 30
       0 1022.81     9.1 1019.84    27.3 1013.18    72.8  995.42    81.8  992.23
     100  986.28   109.1   983.2   118.8  979.63   128.4  975.47     138     971
   146.5  968.02   147.6  967.63   157.2  967.04   166.8  967.76   176.4  969.12
     186  970.04   214.9  971.32   224.5  971.86   253.3  973.65   262.9  974.39
   272.6  975.33   282.2  976.54   291.8  978.22   301.4  980.59     311  983.39
   320.6  986.93   330.2  991.14   339.8  995.85   359.1 1005.58   368.7 1010.03
#Mann= 3 , 0 , 0
       0     .06       0   146.5    .045       0   166.8     .06       0
Bank Sta=146.5,166.8
XS Rating Curve= 0 ,0
Exp/Cntr=0.3,0.1

Type RM Length L Ch R = 1 ,1657.8  ,67.5,61.4,55.7
XS GIS Cut Line= 4
     1664043.256      270683.076     1663774.108      270758.462
     1663718.379      270751.691       1663593.9      270773.045
#Sta/Elev= 30
       0 1034.74    67.5  1030.5    96.4 1029.09     106 1028.23   125.3 1025.37
   144.6 1021.44   163.8 1016.13   183.1 1009.18   202.4 1002.64     212  998.86
   221.7  993.87   231.3  988.48     241   983.6   250.6  979.78   260.2  976.86
   279.5  971.71   298.2  965.17   299.6  964.94   307.6   963.6   316.9   964.5
   326.3  966.22   335.6  967.37   364.8  968.59   374.5  969.58   384.2   972.6
   393.9  977.52   403.6  983.08   442.5 1006.14   452.2 1011.04   461.9 1015.22
#Mann= 3 , 0 , 0
       0     .06       0   299.6    .045       0   316.9     .06       0
Bank Sta=299.6,316.9
XS Rating Curve= 0 ,0
Exp/Cntr=0.3,0.1

Type RM Length L Ch R = 1 ,1596.3  ,202.4,186.9,170.8
XS GIS Cut Line= 4
     1663903.275      270649.607       1663768.9      270690.232
     1663703.275      270699.607     1663593.379      270692.576
#Sta/Elev= 30
       0 1029.39     9.4 1028.19    18.7 1026.69    28.1 1024.84    37.4 1022.48
    46.8 1019.66    56.2  1016.6    65.5 1013.38    74.9 1009.83    84.2 1005.77
    93.6 1001.25   112.3  991.47   121.7  987.04     131  983.63   140.4  979.97
   149.8  974.45   159.3   967.5   168.8  962.78   178.3   961.9   187.7  963.41
   197.2   965.4   206.7  966.67   234.2  967.44   243.4  967.95   252.6  969.24
   261.7  972.05   270.9  976.24   280.1  980.91   298.4  990.53   316.8  999.81
#Mann= 3 , 0 , 0
       0     .06       0   168.8    .045       0   187.7     .06       0
Bank Sta=168.8,187.7
XS Rating Curve= 0 ,0
Exp/Cntr=0.3,0.1

Type RM Length L Ch R = 1 ,1409.5  ,36.8,35.1,33.4
XS GIS Cut Line= 2
      1663700.15      270473.826     1663567.338      270618.357
#Sta/Elev= 22
       0  981.13     9.8  978.83    19.6  975.42    29.4  971.42    39.3  967.63
    49.1  965.45    58.9  964.89    68.7  964.22    78.5  962.56    83.1  961.62
    88.3  960.55    98.1   959.6     108  960.02   117.8  961.71   127.6  963.92
   137.4  966.48   147.2  969.41     157  972.44   166.8  976.27   176.7  981.28
   186.5  986.75   196.3  992.14
#Mann= 3 , 0 , 0
       0     .06       0    83.1    .045       0     108     .06       0
Bank Sta=83.1,108
XS Rating Curve= 0 ,0
Exp/Cntr=0.3,0.1

Type RM Length L Ch R = 1 ,1374.4  ,65.1,76.9,88.6
XS GIS Cut Line= 3
     1663681.921      270429.555      1663575.15      270566.274
     1663525.671      270602.732
#Sta/Elev= 28
       0  971.59     9.6  969.69    19.3  967.93    28.9  966.85    38.6  966.14
    48.2  965.64    57.8   965.1    67.5  964.39    77.1  963.59    86.7  962.63
    96.4  961.18     104  960.06     106  959.76   115.6  959.22     119   959.5
   125.3  960.01   134.9  961.78   144.6  964.29   154.2  967.25   163.8  970.54
   173.5  974.06   182.2   977.6     191  981.42   199.8  985.22   208.6  989.09
   217.4  992.96   226.2  996.92   234.9  1000.8
#Mann= 3 , 0 , 0
       0     .06       0     104    .045       0   125.3     .06       0
Bank Sta=104,125.3
XS Rating Curve= 0 ,0
Exp/Cntr=0.3,0.1

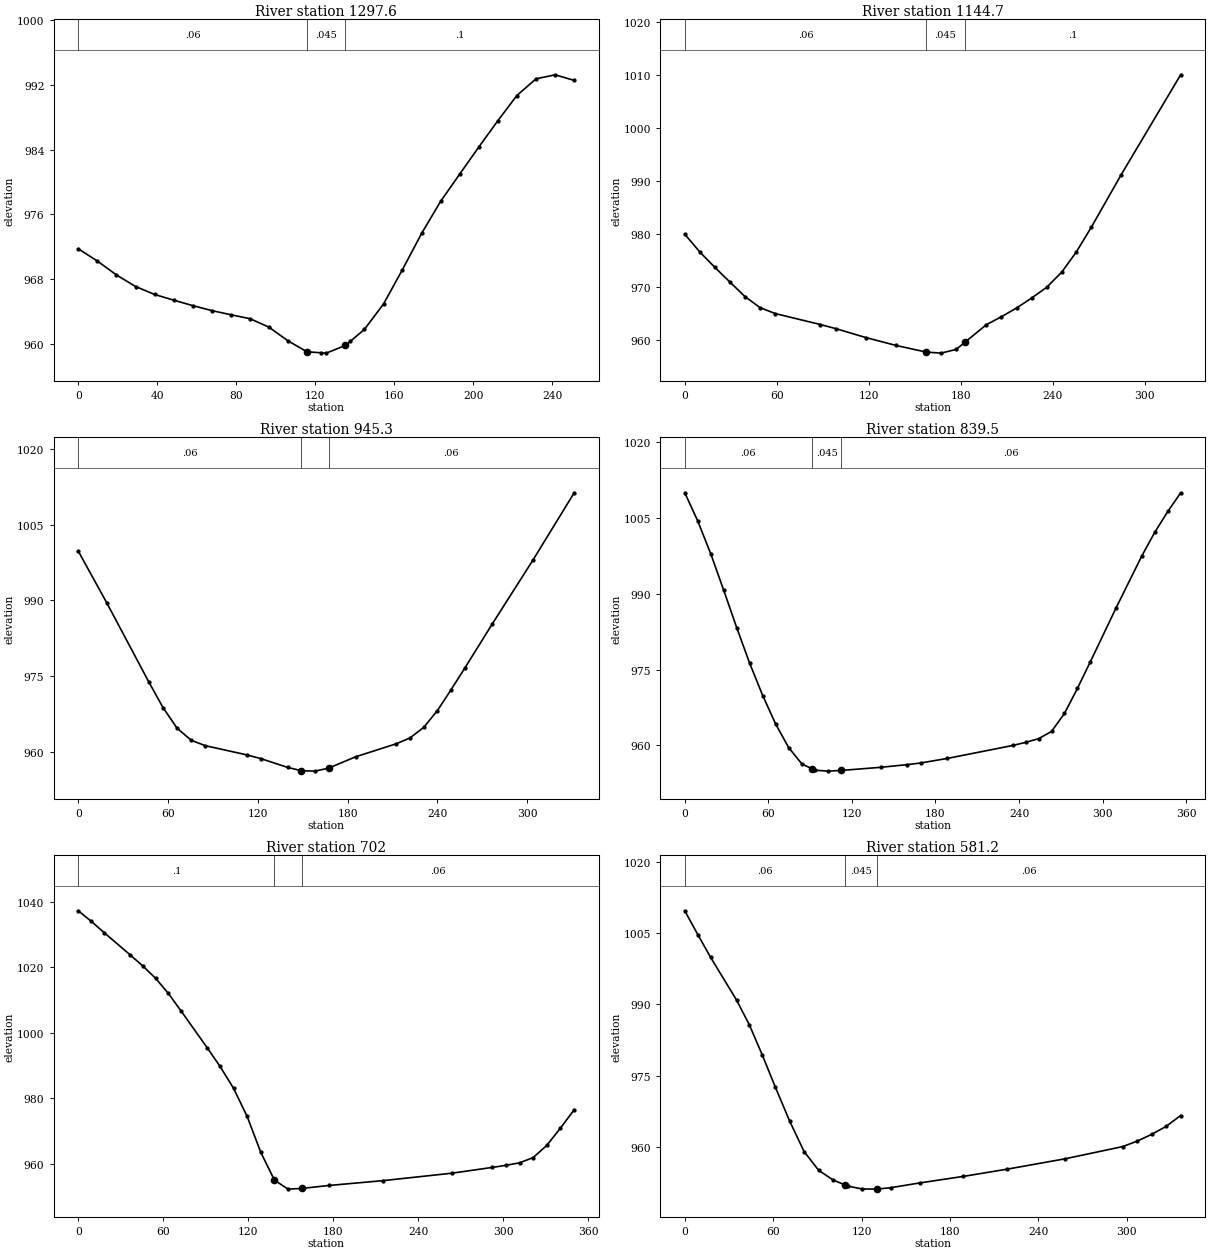
Type RM Length L Ch R = 1 ,1297.6  ,149.4,152.9,156.4
XS GIS Cut Line= 2
     1663680.619      270412.628     1663448.848      270508.982
#Sta/Elev= 29
       0  971.74     9.6  970.24    19.3  968.51      29  967.08    38.6   966.1
    48.3  965.39    57.9  964.72    67.6   964.1    77.2  963.59    86.9   963.1
    96.5  962.05   106.2  960.35   115.8     959   122.6  958.89   125.5  958.84
   135.2  959.79   137.6  960.28   144.8  961.77   154.5  964.92   164.1  969.18
   173.8  973.66   183.4  977.62   193.1     981   202.7  984.33   212.4   987.6
     222  990.71   231.7  992.78   241.4  993.27     251  992.58
#Mann= 3 , 0 , 0
       0     .06       0   115.8    .045       0   135.2      .1       0
Bank Sta=115.8,135.2
XS Rating Curve= 0 ,0
Exp/Cntr=0.3,0.1

Type RM Length L Ch R = 1 ,1144.7  ,186.3,199.4,212.6
XS GIS Cut Line= 3
     1663653.269       270292.47      1663423.85      270347.997
     1663339.144      270326.677
#Sta/Elev= 25
       0  979.99     9.8  976.65    19.7  973.73    29.5  970.97    39.3  968.24
    49.2  966.16      59  965.06    88.5  962.99    98.4  962.23     118  960.55
   137.7  959.06   157.4  957.81   167.2  957.61     177  958.31   182.6  959.63
   196.7  962.96   206.5  964.46   216.4  966.11   226.2  967.98     236  969.99
   245.8  972.84   255.4  976.66   265.2  981.34   284.6  991.18   323.4    1010
#Mann= 3 , 0 , 0
       0     .06       0   157.4    .045       0   182.6      .1       0
Bank Sta=157.4,182.6
XS Rating Curve= 0 ,0
Exp/Cntr=0.3,0.1

Type RM Length L Ch R = 1 ,945.3   ,110.4,105.7,102
XS GIS Cut Line= 4
     1663633.227      270151.249     1663529.689      270158.564
     1663435.827      270124.868     1663310.827      270152.212
#Sta/Elev= 23
       0  999.73    18.9  989.57    47.2   973.8    56.6  968.77      66  964.69
    75.5  962.28    84.9  961.22   112.9  959.38   121.9  958.67   140.1   956.9
   149.1  956.27   158.2  956.18   167.3  956.77   185.4  959.02   212.7  961.61
   221.8  962.77   230.9  964.84   240.1  968.18   249.2  972.31   258.4   976.6
   276.6  985.26   304.1  998.05   331.5  1011.3
#Mann= 3 , 0 , 0
       0     .06       0   149.1    .045       0   167.3     .06       0
Bank Sta=149.1,167.3
XS Rating Curve= 0 ,0
Exp/Cntr=0.3,0.1

Type RM Length L Ch R = 1 ,839.5   ,146.2,137.5,127.7
XS GIS Cut Line= 4
     1663641.764      270057.915     1663567.227       270061.73
     1663409.218      270031.405     1663294.263      270067.582
#Sta/Elev= 30
       0 1010.01     9.3 1004.43    18.7  997.89      28  990.68    37.3   983.3
    46.6  976.25      56  969.85    65.3  964.21    74.6  959.57    84.1  956.33
    91.2  955.41    93.6   955.1     103  954.92   112.5  955.06   140.9  955.68
   159.8  956.21   169.3  956.53   188.2  957.42   235.5     960   244.8  960.62
   254.1  961.35   263.3  962.78   272.6  966.33   281.9   971.3   291.2  976.58
   309.7  987.26   328.2  997.55   337.5 1002.23   346.8 1006.32     356    1010
#Mann= 3 , 0 , 0
       0     .06       0    91.2    .045       0   112.5     .06       0
Bank Sta=91.2,112.5
XS Rating Curve= 0 ,0
Exp/Cntr=0.3,0.1

Type RM Length L Ch R = 1 ,702     ,121.9,120.9,119.7
XS GIS Cut Line= 3
     1663671.382      269926.476     1663571.581      269920.429
     1663328.629      269979.734
#Sta/Elev= 26
       0 1037.16     9.1 1033.98    18.2 1030.52    36.4 1023.81    45.4 1020.41
    54.5 1016.63    63.6 1011.98    72.7 1006.55    90.9  995.49     100   989.8
   109.6  983.07   119.2  974.51   128.8  963.59   138.5  955.08   148.1  952.36
   157.7  952.57   176.9  953.47   215.4  954.96   263.5   957.2   292.4  958.98
     302  959.62   311.6  960.38   321.2  961.99   330.8   965.7   340.4  970.94
   350.1  976.53
#Mann= 3 , 0 , 0
       0      .1       0   138.5    .045       0   157.7     .06       0
Bank Sta=138.5,157.7
XS Rating Curve= 0 ,0
Exp/Cntr=0.3,0.1

Type RM Length L Ch R = 1 ,581.2   ,219.4,216.3,211.6
XS GIS Cut Line= 3
      1663602.31      269806.114     1663540.996      269803.382
     1663277.805      269883.724
#Sta/Elev= 25
       0 1009.71     8.8 1004.72    17.5  999.93    35.1  990.94    43.8  985.72
    52.6  979.36    61.4  972.64    71.2  965.43      81  959.02    90.9  955.07
   100.7  953.05   108.8  951.99   110.5  951.77   120.3  951.16   130.2  951.12
     140  951.43   159.6  952.43   189.1   953.8   218.6  955.31   257.9  957.49
   297.2  960.07   307.1  961.23   316.9  962.64   326.7  964.32   336.6  966.62
#Mann= 3 , 0 , 0
       0     .06       0   108.8    .045       0   130.2     .06       0
Bank Sta=108.8,130.2
XS Rating Curve= 0 ,0
Exp/Cntr=0.3,0.1

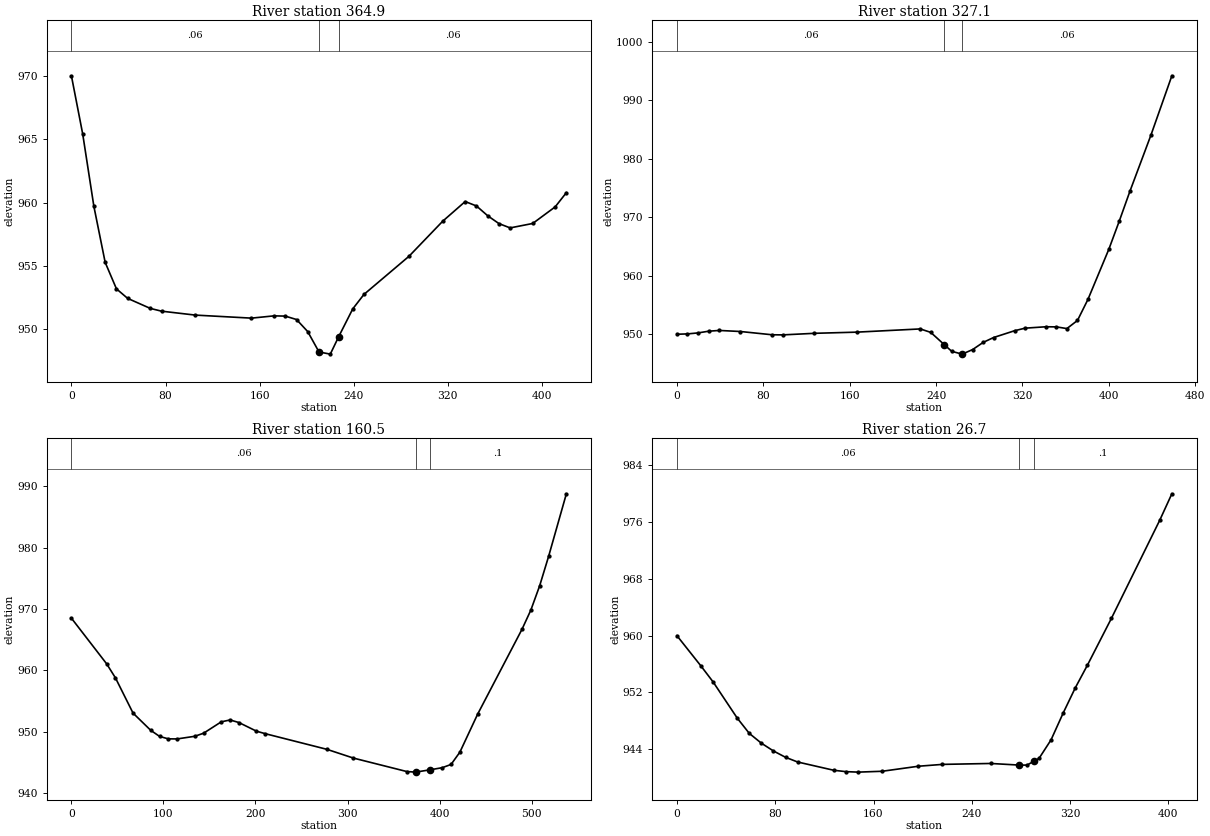
Type RM Length L Ch R = 1 ,364.9   ,38.4,37.8,37.2
XS GIS Cut Line= 3
     1663555.267      269638.518     1663394.247      269661.804
     1663170.723      269790.927
#Sta/Elev= 29
       0     970     9.6  965.41    19.1   959.7    28.7  955.28    38.3  953.19
    47.8  952.44      67  951.65    76.6  951.43   105.3  951.12   153.1  950.88
   172.3  951.06   181.8  951.04   191.4  950.77   200.9  949.82   210.5  948.21
   220.1  948.04   227.2  949.41   239.2  951.61   248.7  952.75     287  955.76
   315.7  958.53   334.8  960.08   344.4  959.73   353.9  958.96   363.5  958.34
     373     958   392.2  958.35   411.3  959.66   420.8  960.78
#Mann= 3 , 0 , 0
       0     .06       0   210.5    .045       0   227.2     .06       0
Bank Sta=210.5,227.2
XS Rating Curve= 0 ,0
Exp/Cntr=0.3,0.1

Type RM Length L Ch R = 1 ,327.1   ,173.3,166.6,159.9
XS GIS Cut Line= 4
     1663557.624      269546.743     1663353.015      269641.187
     1663245.593      269707.377     1663142.511      269735.588
#Sta/Elev= 30
       0     950     9.8  950.06    19.6  950.23    29.4  950.52    39.2  950.65
    58.8  950.47    88.2  949.91      98  949.89   127.4  950.16   166.6  950.36
   225.4  950.91   235.1  950.32   247.7  948.21   254.5  947.08   264.2   946.6
   273.9  947.38   283.6   948.6   293.3  949.44   312.7   950.6   322.4  951.04
   341.8  951.28   351.5  951.26   361.2  950.97     371  952.36   380.7  955.96
   400.1  964.56   409.8   969.4   419.5  974.42     439  984.04   458.4   994.2
#Mann= 3 , 0 , 0
       0     .06       0   247.7    .045       0   264.2     .06       0
Bank Sta=247.7,264.2
XS Rating Curve= 0 ,0
Exp/Cntr=0.3,0.1

Type RM Length L Ch R = 1 ,160.5   ,137.5,133.8,130.1
XS GIS Cut Line= 3
     1663492.989      269309.156     1663249.933      269495.788
     1663095.853      269668.314
#Sta/Elev= 30
       0   968.5    38.3  961.06    47.9  958.76      67  953.03    86.2  950.23
    95.8  949.24   105.3  948.84   114.9  948.83   134.1  949.26   143.6  949.76
   162.8  951.61   172.4  951.92     182   951.5   201.1  950.09   210.7  949.68
   277.7  947.13   306.4  945.71   364.3  943.52   373.9  943.42   374.4  943.43
   389.4  943.79   402.8  944.14   412.5  944.67   422.1  946.67   441.4  952.86
   489.6  966.69   499.2  969.81   508.8  973.78   518.5  978.56   537.8  988.76
#Mann= 3 , 0 , 0
       0     .06       0   374.4    .045       0   389.4      .1       0
Bank Sta=374.4,389.4
XS Rating Curve= 0 ,0
Exp/Cntr=0.3,0.1

Type RM Length L Ch R = 1 ,26.7    ,33,26.7,20.4
XS GIS Cut Line= 2
     1663236.056      269244.013     1663021.992       269585.18
#Sta/Elev= 27
       0     960    19.6  955.72    29.5  953.47    49.1  948.38    58.9  946.23
    68.8  944.84    78.6  943.75    88.4  942.86    98.2   942.2   127.7  941.03
   137.5  940.84   147.4  940.77     167  940.89   196.5   941.6   216.1  941.86
   255.4  941.99   278.8  941.76   284.9  941.76  290.28942.2738   294.7   942.7
   304.5  945.32   314.4  949.11   324.2  952.64     334  955.81   353.6  962.43
   392.9  976.24   402.8  979.98
#Mann= 3 , 0 , 0
       0     .06       0   278.8    .045       0  290.28      .1       0
Bank Sta=278.8,290.28
XS Rating Curve= 0 ,0
Exp/Cntr=0.3,0.1

Chan Stop Cuts=-1
Use User Specified Reach Order=0
Composite Channel Slope=5